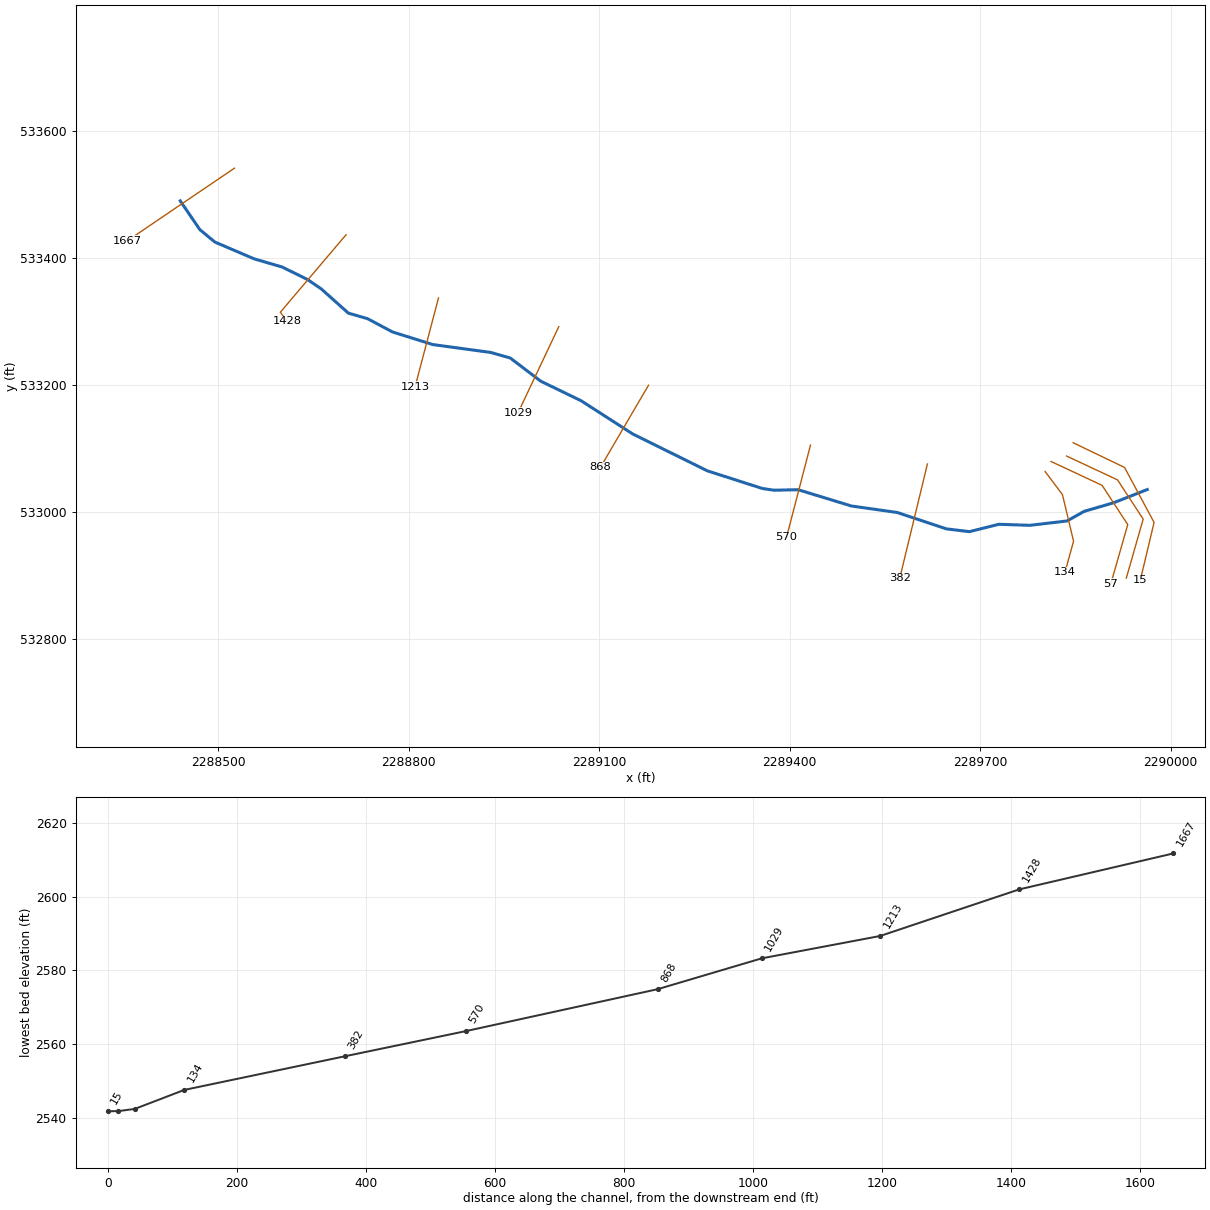
--- TROUTRN.prj (project) ---

Proj Title=TROUTRN
Current Plan=p01
Default Exp/Contr=0,0
English Units
Geom File=g01
Flow File=f01
Plan File=p01
Background Map Layer=Inundation Boundary (01pct Value_0)
BEGIN DESCRIPTION:
----------MODEL BY WOOD PLC 2021----------
Stream Name: Trout Run
Flood Zone: Enhanced Approximate
Pocahontas County, WV
HEC-RAS Version: RAS 6.1
Vertical Datum: NAVD88
Projection: NAD 1983 StatePlane West Virginia S FIPS 4702 (US Feet)
Terrain: 1-meter LIDAR (FEMA Region III 3DEP collected 2016-2018)
Land Use: 2019 NLCD
Hydrologic Method:
WV SIR2010-5033 regression equations
Model Notes:
Normal depth tie in to Greenbrier River
END DESCRIPTION:
DSS Export Rating Curves= 0
DSS Export Rating Curve Sorted= 0
DSS Export Volume Flow Curves= 0
DXF OffsetX= 0
DXF OffsetY= 0
DXF ScaleX= 0
DXF ScaleY= 0

--- TROUTRN.p01 (plan) ---

Plan Title=Floodplain
Program Version=6.10
Short Identifier=Floodplain
Geom File=g01
Flow File=f01
Subcritical Flow
K Sum by GR= 0
Std Step Tol= 0.01
Critical Tol= 0.01
Num of Std Step Trials= 20
Max Error Tol= 0.3
Flow Tol Ratio= 0.001
Split Flow NTrial= 30
Split Flow Tol= 0.02
Split Flow Ratio= 0.02
Log Output Level= 0
Friction Slope Method= 1
Unsteady Friction Slope Method= 2
Unsteady Bridges Friction Slope Method= 1
Parabolic Critical Depth
Global Vel Dist= 0 , 0 , 0
Global Log Level= 0
CheckData=False
Encroach Param=-1 ,0,0, 0
Mapping Interval=1HOUR
Computation Time Step Use Courant=        0
Computation Time Step Use Time Series=    0
Computation Time Step Count To Double=0
Computation Time Step Max Doubling=0
Computation Time Step Max Halving=0
Computation Time Step Residence Courant=0
Run HTab= 0
Run UNet= 0
Run Sediment= 0
Run PostProcess= 0
Run WQNet= 0
Run RASMapper=-1
UNET Theta= 0
UNET Theta Warmup= 0
UNET ZTol= 0
UNET ZSATol= 0
UNET MxIter= 0
UNET Max Iter WO Improvement= 0
UNET MaxInSteps= 0
UNET DtIC= 0
UNET DtMin= 0
UNET MaxCRTS= 0
UNET WFStab= 0
UNET SFStab= 0
UNET WFX= 1
UNET SFX= 1
UNET Gravity=32.174
UNET 1D Methodology=Finite Difference
UNET DSS MLevel= 1
UNET Pardiso=0
UNET DZMax Abort= 0
UNET Use Existing IB Tables= 0
UNET Froude Reduction=False
UNET Froude Limit= 0
UNET Froude Power= 0
UNET D1 Cores= 0
UNET WindReference=Eulerian
UNET WindDragFormulation=Hsu (1988)
UNET D2 Coriolis=0
UNET D2 Cores= 0
UNET D2 Theta= 1
UNET D2 Theta Warmup= 1
UNET D2 Z Tol= 0.01
UNET D2 Volume Tol= 0.01
UNET D2 Max Iterations= 20
UNET D2 Equation= 0
UNET D2 RampUpFraction=0.1
UNET D2 TimeSlices= 1
UNET D2 Turbulence Formulation=Non-Conservative (original)
UNET D2 Eddy Viscosity=0.3
UNET D2 Transverse Eddy Viscosity=0.1
UNET D2 Smagorinsky Mixing=0
UNET D2 BCVolumeCheck=0
UNET D2 Cores=0
UNET D2 SolverType=PARDISO (Direct)
UNET D2 Minimum Iterations= 2147483647
UNET D2 Maximum Iterations= 2147483647
UNET D2 Restart Number= 10
UNET D2 Relaxation Coeff=1.3
UNET D2 SOR Precondition Iterations= 10
UNET D2 ILUT Maximum Fill= 8
UNET D2 ILUT Tolerance=1E-08
UNET D1D2 MaxIter= 0
UNET D1D2 ZTol=0.01
UNET D1D2 QTol=0.1
UNET D1D2 MinQTol=1
Write IC File= 0
Write IC File at Fixed DateTime=0
Write IC File at Sim End=0
Echo Input=False
Echo Parameters=False
Echo Output=False
Write Detailed= 0
HDF Write Warmup=0
HDF Write Time Slices=0
HDF Flush=0
HDF Compression= 1
HDF Chunk Size= 1
HDF Spatial Parts= 1
HDF Use Max Rows=0
HDF Fixed Rows= 1
Calibration Method= 0
Calibration Iterations= 20
Calibration Max Change=0.05
Calibration Tolerance=0.2
Calibration Maximum=1.5
Calibration Minimum=0.5
Calibration Optimization Method= 1
WQ AD Non Conservative
WQ ULTIMATE=-1
WQ Max Comp Step=1HOUR
WQ Output Interval=15MIN
WQ Output Selected Increments= 0
WQ Output face flow=0
WQ Output face velocity=0
WQ Output face area=0
WQ Output face dispersion=0
WQ Output cell volume=0
WQ Output cell surface area=0
WQ Output cell continuity=0
WQ Output cumulative cell continuity=0
WQ Output face conc=0
WQ Output face dconc_dx=0
WQ Output face courant=0
WQ Output face peclet=0
WQ Output face adv mass=0
WQ Output face disp mass=0
WQ Output cell mass=0
WQ Output cell source sink temp=0
WQ Output nsm pathways=0
WQ Output nsm derived pathways=0
WQ Create Restart=0
WQ Fixed Restart=0
WQ System Summary=0
WQ Write To DSS=0
Sorting and Armoring Iterations= 10
XS Update Threshold= 0.02
Bed Roughness Predictor= 0
Hydraulics Update Threshold= 0.02
Energy Slope Method= 1
Volume Change Method= 1
Sediment Retention Method= 0
Sediment TS Multiplier= 1
Warm Up Method= 0
XS Weighting Method= 0
Number of US Weighted Cross Sections= 1
Number of DS Weighted Cross Sections= 1
Upstream XS Weight=0
Main XS Weight=1
Downstream XS Weight=0
Number of DS XS's Weighted with US Boundary= 1
Upstream Boundary Weight= 1
Weight of XSs Associated with US Boundary= 0
Number of US XS's Weighted with DS Boundary= 1
Downstream Boundary Weight= 0.5
Weight of XSs Associated with DS Boundary= 0.5
Percentile Method= 0
Sediment Output Level= 3
Mass or Volume Output= 0
Output Increment Type= 1
Profile and TS Output Increment= 1
Transport Output Increment 1
XS Output Flag= 0
XS Output Increment= 10
Read HDF5 Sediment Hotstart= 0
Sediment Hotstart Type= 0
Write Gradation File= 0
Read Gradation Hotstart= 0
Write HDF5 File= 1
Write Binary Output= 1
Write DSS Sediment File= 0
DSS Sediment Output Type= 1
SV Curve= 0
Specific Gage Flag= 0
Subcell Erosion Methods= 0
Subcell Deposition Methods= 0
Advection Scheme= 1
Matrix Solver= 0
Implicit Weighting Factor= 1
Maximum Outer Loop Convergence Iterations= 5
Convergence Maximum Absolute= 0.001
Convergence RMSE= 0.0001
Grain Fractions Max Abs Error= 0.001
Max Subgrid Regions= 1
Max Subgrid Length Scale= 3.402823E+38
Initial Layer Thickness= 3.402823E+38
Min Layer Thickness= 3.402823E+38
Max Layer Thickness= 3.402823E+38
Number of Layers= 5

--- TROUTRN.f01 (steady flow) ---

Flow Title=Flow
Program Version=6.10
Number of Profiles= 6
Profile Names=01pct,10pct,04pct,02pct,0_2pct,01plus
River Rch & RM=TROUTRN,Main            ,1667
     531     280     373     449     743     785
Boundary for River Rch & Prof#=TROUTRN,Main            , 1
Up Type= 0
Dn Type= 3
Dn Slope=0.02164
Boundary for River Rch & Prof#=TROUTRN,Main            , 2
Up Type= 0
Dn Type= 3
Dn Slope=0.02164
Boundary for River Rch & Prof#=TROUTRN,Main            , 3
Up Type= 0
Dn Type= 3
Dn Slope=0.02164
Boundary for River Rch & Prof#=TROUTRN,Main            , 4
Up Type= 0
Dn Type= 3
Dn Slope=0.02164
Boundary for River Rch & Prof#=TROUTRN,Main            , 5
Up Type= 0
Dn Type= 3
Dn Slope=0.02164
Boundary for River Rch & Prof#=TROUTRN,Main            , 6
Up Type= 0
Dn Type= 3
Dn Slope=0.02164
DSS Import GetInterval= 0
DSS Import GetPeak= 0
DSS Import FillOption= 0

--- TROUTRN.g01 (geometry) ---

Geom Title=Geometry
Program Version=6.10

River Reach=TROUTRN         ,Main
Reach XY= 30
     2288439.776      533490.553     2288470.582      533445.401
     2288494.206      533425.807     2288556.362      533399.233
     2288600.233      533386.478     2288640.219      533366.749
     2288661.786      533352.025     2288704.543      533313.857
     2288734.772      533305.041      2288774.21      533284.117
      2288837.71       533264.252288928.67842799533251.879445373
2288959.64117428533243.106667258 2289007.7719804533206.505268821
2289071.27774796533175.7446626572289152.64451266533123.402018297
     2289270.215      533065.302     2289356.867      533037.514
     2289375.276      533034.788     2289413.168      533035.594
     2289497.155      533009.927      2289569.48      532999.681
     2289646.499      532973.922     2289683.074      532969.525
     2289729.438      532981.131     2289778.273      532979.489
     2289836.761      532986.358     2289863.838      533001.495
     2289910.715      533015.203     2289963.216       533035.87

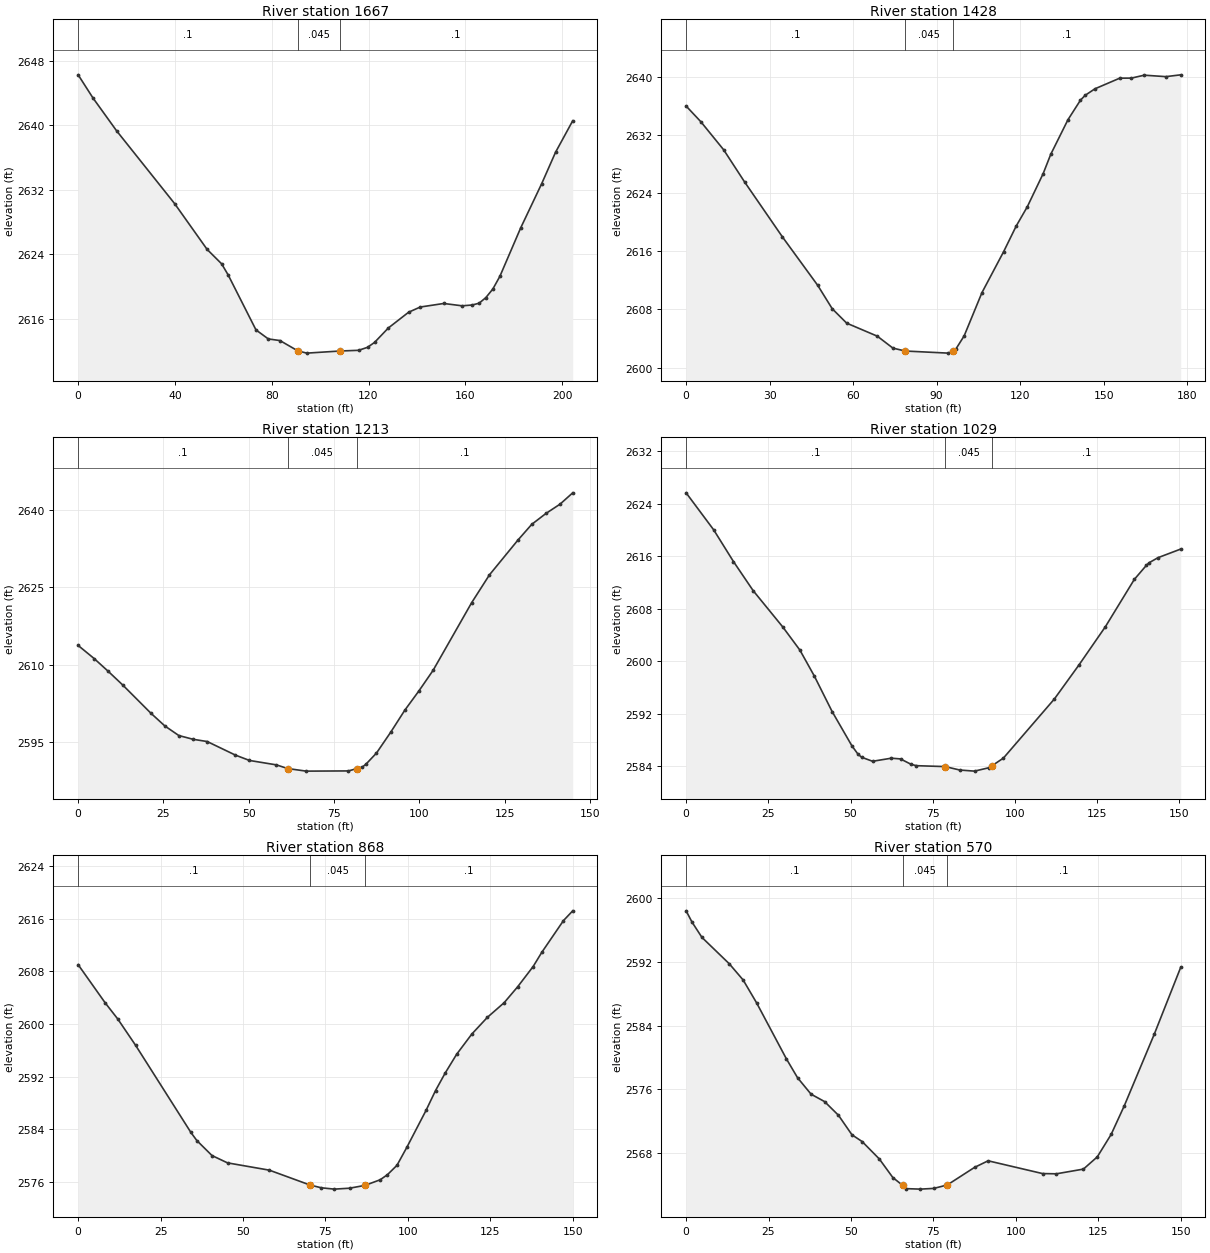
Type RM Length L Ch R = 1 ,1667    ,239.1,239.1,239.1
XS GIS Cut Line= 2
2288525.22391817533542.2219442112288356.07558196533427.545106103
#Sta/Elev= 30
       0 2646.28     6.1 2643.42    15.9 2639.33    39.9 2630.29    53.3 2624.62
    59.3 2622.83      62 2621.45    73.5 2614.63    78.6 2613.51    83.4 2613.31
    90.8 2612.03    94.5 2611.75   108.1 2612.01   115.9  2612.1   119.6 2612.47
   122.5 2613.08   128.2 2614.87   136.6 2616.83   141.4 2617.47   151.1 2617.91
   158.7 2617.62   162.8 2617.72   165.7 2617.94   168.5 2618.64   171.4 2619.71
   174.3 2621.28   182.9 2627.29   191.6 2632.79   197.3 2636.67   204.4 2640.58
#Mann= 3 ,0,0
       0      .1       0    90.8    .045       0   108.1      .1       0
Bank Sta=90.8,108.1
XS Rating Curve= 0 ,0
Exp/Cntr(USF)=0,0
Exp/Cntr=0.3,0.1

Type RM Length L Ch R = 1 ,1428    ,207.2,215.6,220.4
XS GIS Cut Line= 3
2288700.92039328533437.2191649922288597.42961909 533315.19768539
2288607.91394836533300.909917997
#Sta/Elev= 30
       0 2635.95     5.3 2633.79    13.5 2629.93      21 2625.52    34.6 2617.96
    47.3 2611.29    52.5 2608.08    57.7  2606.1    68.7 2604.31    74.3 2602.67
    78.7 2602.27    94.2 2601.98   95.83 2602.29      97 2602.59    99.9 2604.35
   106.3  2610.3   114.1 2615.94   118.6 2619.45   122.6 2622.11   128.3 2626.67
     131  2629.3   137.2 2634.07   141.7 2636.76   143.4 2637.43   146.9 2638.32
   155.8 2639.78     160 2639.79   164.6 2640.19   172.4 2639.99   177.7 2640.24
#Mann= 3 ,-1,0
       0      .1       0    78.7    .045       0   95.83      .1       0
Bank Sta=78.7,95.83
XS Rating Curve= 0 ,0
Exp/Cntr(USF)=0,0
Exp/Cntr=0.3,0.1

Type RM Length L Ch R = 1 ,1213    ,185.7,183.5,181.5
XS GIS Cut Line= 2
 2288846.6123676533337.7331729472288809.66094199533197.572593036
#Sta/Elev= 30
       0  2613.7     4.7 2611.15     8.8 2608.69      13 2606.07    21.3 2600.57
    25.4 2598.09    29.5 2596.23    33.7  2595.5    37.8 2595.07    46.1 2592.43
    50.2  2591.4    58.1 2590.54    61.4 2589.83    66.8 2589.33    79.2 2589.37
    81.6 2589.81    83.3 2590.14    84.3 2590.66    87.4 2592.83    91.6  2596.9
    95.7 2601.14    99.9 2604.94     104 2608.88   115.3    2622   120.5 2627.38
   128.8 2634.09   132.9 2637.18   137.1 2639.31   141.2  2641.1   144.9 2643.29
#Mann= 3 ,0,0
       0      .1       0    61.4    .045       0    81.6      .1       0
Bank Sta=61.4,81.6
XS Rating Curve= 0 ,0
Exp/Cntr(USF)=0,0
Exp/Cntr=0.3,0.1

Type RM Length L Ch R = 1 ,1029    ,162.5,161.3,160.3
XS GIS Cut Line= 2
2289036.08796358 533292.410776152288971.73005926533156.451649884
#Sta/Elev= 30
       0 2625.66     8.4 2620.01    14.4 2615.19    20.4 2610.75    29.4 2605.22
    34.6  2601.7      39 2597.74    44.4 2592.34    50.4 2587.13    52.3 2585.82
    53.4 2585.37    56.7 2584.76    62.4 2585.23    65.2 2585.12    68.4  2584.3
      70 2584.09    78.8 2583.95    83.2 2583.43    87.7 2583.26    92.1 2583.78
      93 2584.07    96.5 2585.25     112 2594.26   119.5 2599.46   127.5 2605.26
   136.3 2612.47     140 2614.63   140.8 2615.01   143.5 2615.78   150.4 2617.09
#Mann= 3 ,0,0
       0      .1       0    78.8    .045       0      93      .1       0
Bank Sta=78.8,93
XS Rating Curve= 0 ,0
Exp/Cntr(USF)=0,0
Exp/Cntr=0.3,0.1

Type RM Length L Ch R = 1 ,868     ,293.8,297.5,300.8
XS GIS Cut Line= 2
2289177.47349318533200.2321863082289101.66754548533070.797035388
#Sta/Elev= 30
       0 2608.99     8.2 2603.19      12 2600.75    17.4 2596.76    34.2  2583.5
      36 2582.27    40.6 2579.99    45.3 2578.88      58 2577.77    70.4  2575.5
    73.8 2575.09    77.7 2574.89    82.3 2575.03      87 2575.46    91.6 2576.31
    93.8 2577.08    96.7 2578.51    99.7 2581.25   105.5 2586.84   108.4 2589.87
   111.3 2592.51   114.8 2595.38   119.4 2598.45   124.1 2600.98   129.2 2603.21
   133.3 2605.63     138 2608.71   140.6 2610.85   147.2 2615.69     150 2617.17
#Mann= 3 ,0,0
       0      .1       0    70.4    .045       0      87      .1       0
Bank Sta=70.4,87
XS Rating Curve= 0 ,0
Exp/Cntr(USF)=0,0
Exp/Cntr=0.3,0.1

Type RM Length L Ch R = 1 ,570     ,187.7,188,188.2
XS GIS Cut Line= 2
2289432.63012904533105.8485287542289394.89527453532960.672495075
#Sta/Elev= 30
       0 2598.38     1.8 2596.96     4.8 2595.05    13.1 2591.74    17.3 2589.71
    21.4 2586.83    30.4 2579.84    33.8 2577.46    37.9  2575.4      42 2574.47
    46.2 2572.76    50.3 2570.31    53.4 2569.46    58.6 2567.28    62.7 2564.95
   65.66 2563.98    66.8 2563.56      71  2563.5    75.1 2563.59    79.2 2564.02
    87.5 2566.23    91.6 2567.05   108.1 2565.45   112.3 2565.42   120.5 2566.01
   124.7 2567.54   128.9 2570.35   132.9 2573.95     142 2582.93     150 2591.29
#Mann= 3 ,-1,0
       0      .1       0   65.66    .045       0    79.2      .1       0
Bank Sta=65.66,79.2
XS Rating Curve= 0 ,0
Exp/Cntr(USF)=0,0
Exp/Cntr=0.3,0.1

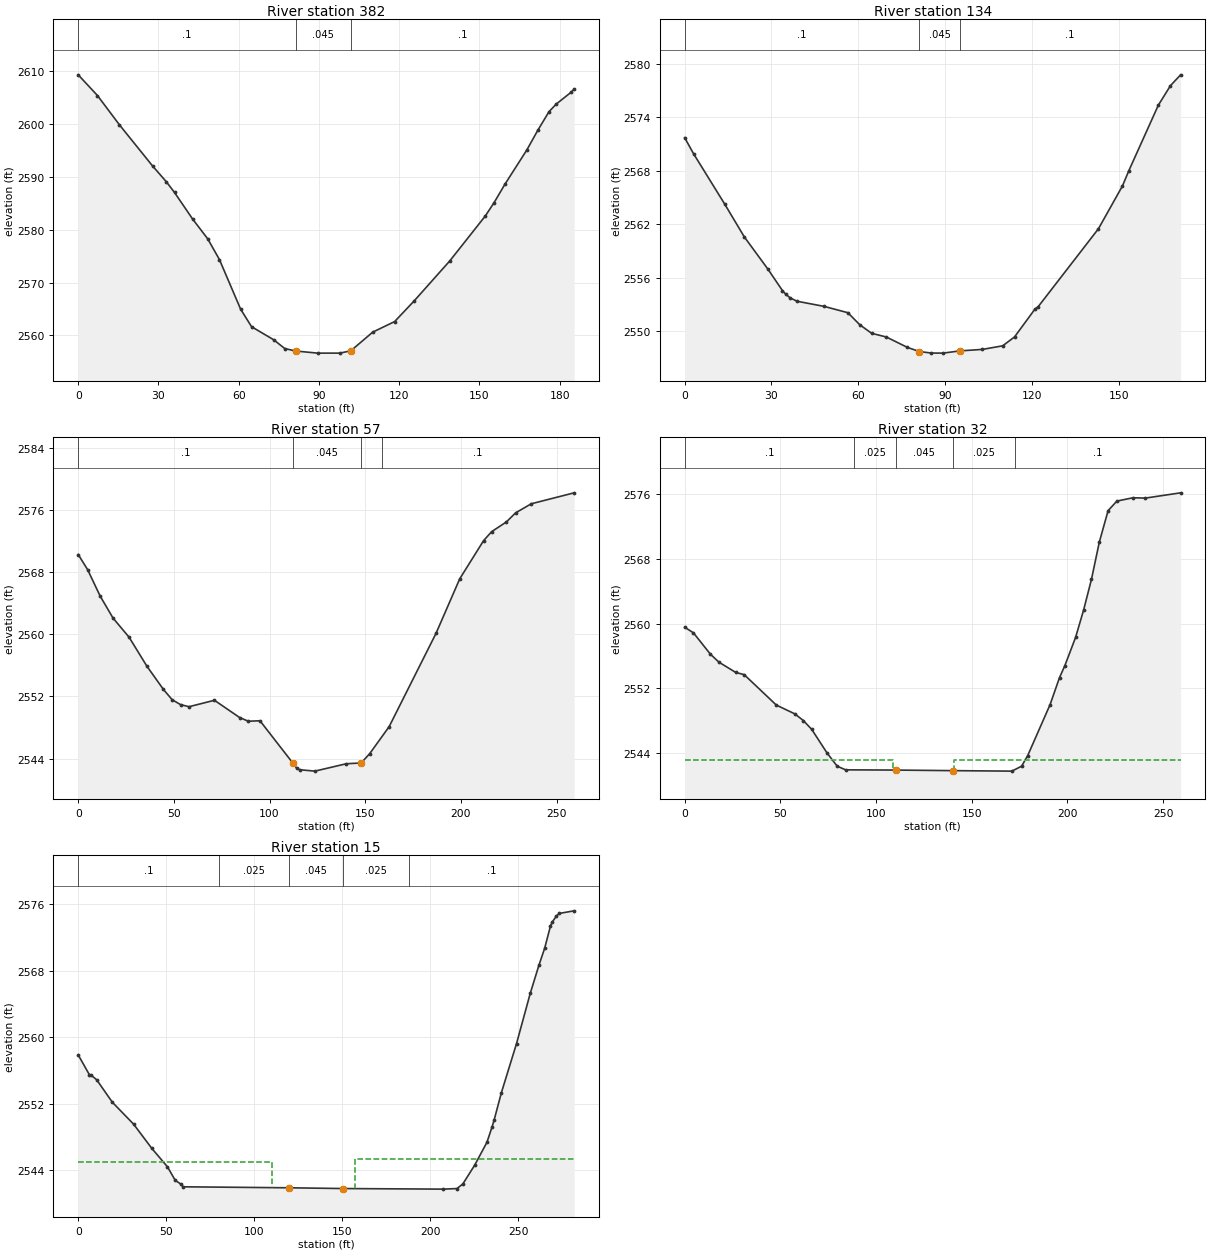
Type RM Length L Ch R = 1 ,382     ,243.1,248.5,255.9
XS GIS Cut Line= 2
2289616.86463441533076.1919993112289573.20716214532895.988815907
#Sta/Elev= 30
       0 2609.29     7.2 2605.37    15.4 2599.84    27.8 2592.05    32.9 2589.09
      36 2587.04    42.8 2581.99    48.4 2578.28    52.8 2574.34    60.7 2564.98
    64.8 2561.65    73.1 2559.17    77.2 2557.52    81.3 2557.05    89.5 2556.65
    97.8 2556.65   101.9 2557.09   110.1 2560.62   118.3 2562.62   125.7 2566.59
   138.9 2574.09   152.2  2582.6   155.5 2585.14   159.5 2588.58   167.7 2595.07
   171.8 2598.79     176 2602.32   178.7 2603.76   184.2 2605.97   185.4 2606.58
#Mann= 3 ,0,0
       0      .1       0    81.3    .045       0   101.9      .1       0
Bank Sta=81.3,101.9
XS Rating Curve= 0 ,0
Exp/Cntr(USF)=0,0
Exp/Cntr=0.3,0.1

Type RM Length L Ch R = 1 ,134     ,72,76.6,87
BEGIN DESCRIPTION:
structure xs 4
END DESCRIPTION:
XS GIS Cut Line= 4
2289802.32798903 533064.202912272289829.57870142  533027.8901151
2289847.08605932532954.4300865422289833.60461182532905.807001323
#Sta/Elev= 30
       0 2571.73     3.1 2569.91    13.8 2564.29    20.6 2560.59    28.8 2556.95
    33.8 2554.55    34.9 2554.16    36.4 2553.75    38.8 2553.36    48.2 2552.78
    56.4 2552.07    60.5 2550.72    64.6 2549.76    69.7 2549.34      77 2548.17
    81.1 2547.71    85.2 2547.54    89.3 2547.5395.006712547.777   102.9 2547.95
   109.9 2548.35     114 2549.35     121 2552.45   122.2 2552.76     143  2561.5
   151.3 2566.31   153.5 2568.02   163.7 2575.38   167.9 2577.58   171.4 2578.79
#Mann= 3 ,0,0
       0      .1       0    81.1    .045       095.00671      .1       0
Bank Sta=81.1,95.00671
XS Rating Curve= 0 ,0
Exp/Cntr(USF)=0,0
Exp/Cntr=0.5,0.3

Type RM Length L Ch R = 1 ,57      ,25.4,25.6,25.1
BEGIN DESCRIPTION:
structure xs 3; 8 ft between structure and xs
END DESCRIPTION:
XS GIS Cut Line= 4
2289811.69751547533080.0512064972289892.05337454533042.435067173
2289932.45975845532980.6643883262289905.87466303532887.709981221
#Sta/Elev= 30
       0 2570.29     4.9 2568.35    11.5 2564.92    18.2  2562.1    26.6 2559.63
    35.9  2555.9    44.5 2552.92    49.1 2551.58    53.5 2550.95    57.9 2550.68
    71.2 2551.51    84.4 2549.28    88.9 2548.81      95 2548.87  112.05 2543.46
   114.1 2542.77   115.7 2542.56   123.7 2542.38   140.1 2543.33   147.9 2543.43
   152.4 2544.65   162.5 2548.11     187 2560.13   199.4 2567.16   211.9 2572.09
   216.1 2573.24   223.8 2574.49   228.6 2575.66   236.8 2576.83   259.2 2578.24
#Mann= 4 ,-1,0
       0      .1       0  112.05    .045       0   147.9    .025       0
  158.72      .1       0
#XS Ineff= 2 , 0
             104  2543.4     156          2543.4
Permanent Ineff=
       F       F
Bank Sta=112.05,147.9
XS Rating Curve= 0 ,0
Exp/Cntr(USF)=0,0
Exp/Cntr=0.5,0.3

Type RM Length L Ch R = 1 ,32      ,17.9,16.3,14.4
BEGIN DESCRIPTION:
structure xs 2; 5.5 ft betweeen structure and xs
END DESCRIPTION:
XS GIS Cut Line= 4
 2289836.0052202533088.6867490122289916.36107927533051.070609688
2289956.76746318532989.2999308412289930.18236776532896.345523736
#Sta/Elev= 30
       0 2559.56     4.6 2558.86    13.4 2556.24    17.9 2555.24    26.7 2553.97
    31.1  2553.7    47.9 2549.94    57.6 2548.85      62 2548.03    66.4 2546.94
    74.3 2544.06    79.7 2542.39    84.1 2541.94   110.2 2541.91  140.12 2541.84
     171 2541.78   176.1 2542.39   179.3 2543.71     191 2550.01   195.9 2553.33
   198.7 2554.81   204.3  2558.3   208.5 2561.68   212.6 2565.47   216.7 2570.06
   221.3 2573.96   225.9 2575.14   234.3 2575.55   240.8 2575.51   259.2 2576.16
#Mann= 5 ,-1,0
       0      .1       0   88.72    .025       0   110.2    .045       0
  140.12    .025       0  172.54      .1       0
#XS Ineff= 2 , 0
             109  2543.2     141          2543.2
Permanent Ineff=
       F       F
Bank Sta=110.2,140.12
XS Rating Curve= 0 ,0
Exp/Cntr(USF)=0,0
Exp/Cntr=0.5,0.3

Type RM Length L Ch R = 1 ,15      ,,,
BEGIN DESCRIPTION:
structure xs 1
END DESCRIPTION:
XS GIS Cut Line= 4
2289846.49868617533109.5621296752289927.40956639533070.699423427
2289973.91739518  532984.05470132289952.25621465532892.950324358
#Sta/Elev= 30
       0 2557.88     6.3 2555.52     7.5 2555.42    10.5 2554.89    19.4 2552.19
    31.5 2549.55    41.8 2546.65    50.7 2544.43    55.1 2542.81    58.5 2542.33
    59.5 2542.03  119.98 2541.91  150.46 2541.82   207.5 2541.75   215.2 2541.82
   218.5 2542.37   225.2 2544.62   232.2 2547.38   235.1 2549.22   236.3 2550.07
   240.4 2553.34     249 2559.24   256.8 2565.28   261.7 2568.64     265 2570.71
   268.3 2573.38   269.2 2573.82   271.7 2574.58   273.3 2574.89281.7418  2575.2
#Mann= 5 ,-1,0
       0      .1       0      80    .025       0  119.98    .045       0
  150.46    .025       0   188.1      .1       0
#XS Ineff= 2 , 0
          109.87    2545  157.43         2545.42
Permanent Ineff=
       F       F
Bank Sta=119.98,150.46
XS Rating Curve= 0 ,0
Exp/Cntr(USF)=0,0
Exp/Cntr=0.3,0.1
LCMann Table=0

Chan Stop Cuts=-1
Use User Specified Reach Order=0
Composite Channel Slope=5